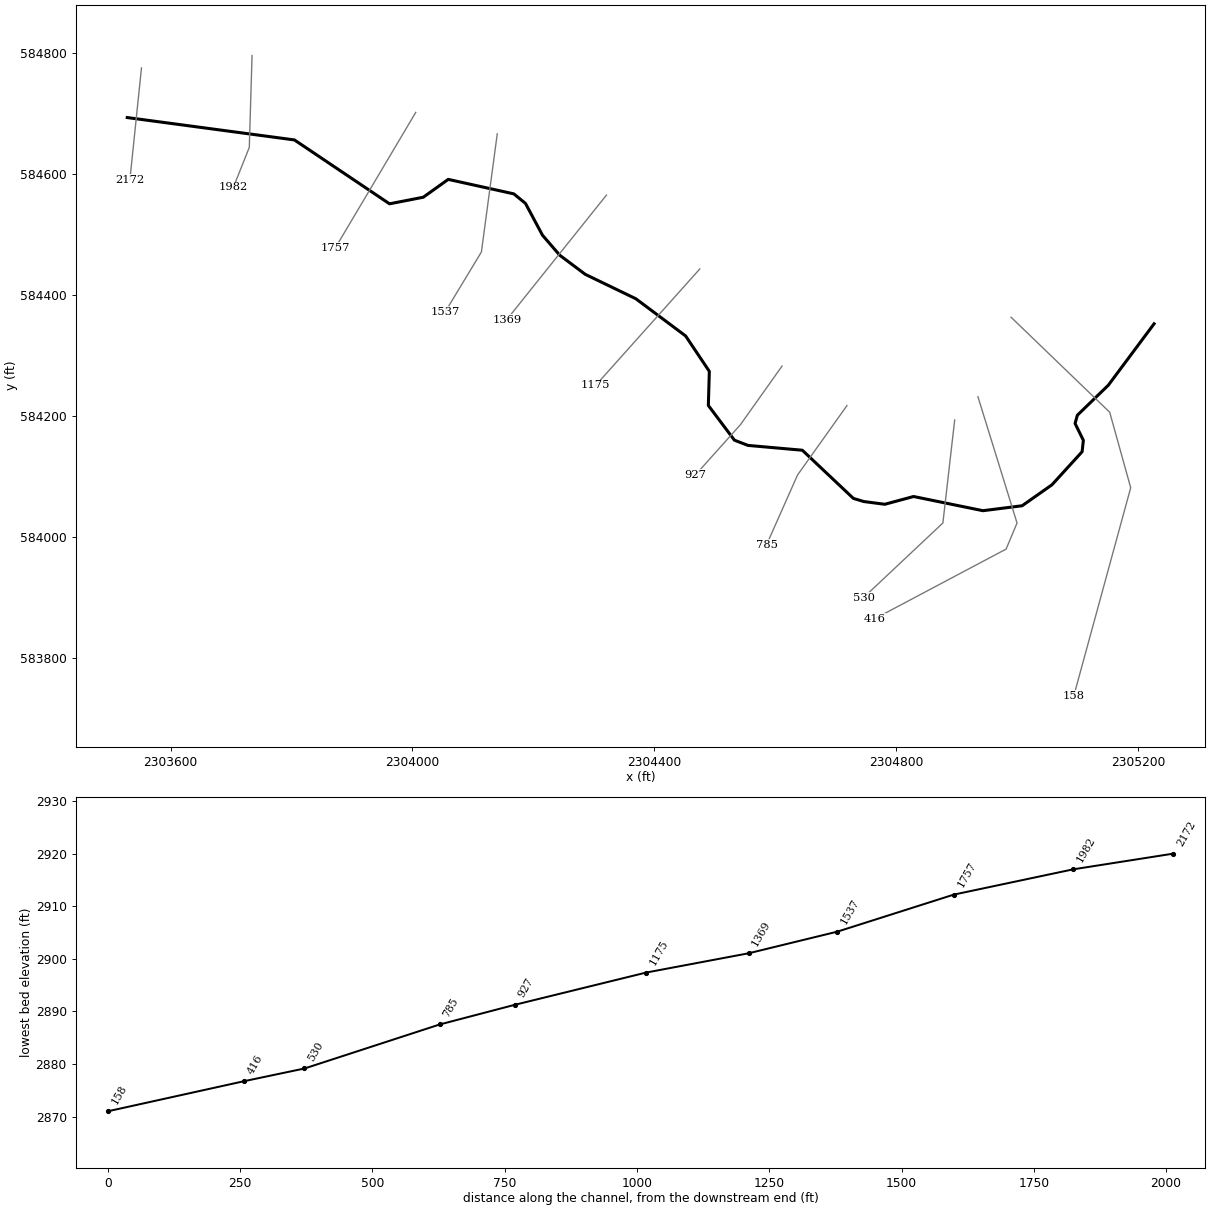
--- GRNBRRRVT1.prj (project) ---

Proj Title=GRNBRRRVT1
Current Plan=p01
Default Exp/Contr=0,0
English Units
Geom File=g01
Flow File=f01
Plan File=p01
BEGIN DESCRIPTION:
----------MODEL BY WOOD PLC 2021----------
Stream Name: West Fork Greenrbrier River Tributary 1
Flood Zone: Enhanced Approximate
Pocahontas County, WV
HEC-RAS Version: RAS 6.1
Vertical Datum: NAVD88
Projection: NAD 1983 StatePlane West Virginia S FIPS 4702 (US Feet)
Terrain: 1-meter LIDAR (FEMA Region III 3DEP collected 2016-2018)
Land Use: 2019 NLCD
Hydrologic Method:
WV SIR2010-5033 regression equations
Model Notes:
END DESCRIPTION:
DSS Export Rating Curves= 0
DSS Export Rating Curve Sorted= 0
DSS Export Volume Flow Curves= 0
DXF OffsetX= 0
DXF OffsetY= 0
DXF ScaleX= 0
DXF ScaleY= 0

--- GRNBRRRVT1.p01 (plan) ---

Plan Title=Floodplain
Program Version=6.10
Short Identifier=Floodplain
Geom File=g01
Flow File=f01
Subcritical Flow
K Sum by GR= 0
Std Step Tol= 0.01
Critical Tol= 0.01
Num of Std Step Trials= 20
Max Error Tol= 0.3
Flow Tol Ratio= 0.001
Split Flow NTrial= 30
Split Flow Tol= 0.02
Split Flow Ratio= 0.02
Log Output Level= 0
Friction Slope Method= 1
Unsteady Friction Slope Method= 2
Unsteady Bridges Friction Slope Method= 1
Parabolic Critical Depth
Global Vel Dist= 0 , 0 , 0
Global Log Level= 0
CheckData=False
Encroach Param=-1 ,0,0, 0
Mapping Interval=1HOUR
Computation Time Step Use Courant=        0
Computation Time Step Use Time Series=    0
Computation Time Step Count To Double=0
Computation Time Step Max Doubling=0
Computation Time Step Max Halving=0
Computation Time Step Residence Courant=0
Run HTab= 0
Run UNet= 0
Run Sediment= 0
Run PostProcess= 0
Run WQNet= 0
Run RASMapper=-1
UNET Theta= 0
UNET Theta Warmup= 0
UNET ZTol= 0
UNET ZSATol= 0
UNET MxIter= 0
UNET Max Iter WO Improvement= 0
UNET MaxInSteps= 0
UNET DtIC= 0
UNET DtMin= 0
UNET MaxCRTS= 0
UNET WFStab= 0
UNET SFStab= 0
UNET WFX= 1
UNET SFX= 1
UNET Gravity=32.174
UNET 1D Methodology=Finite Difference
UNET DSS MLevel= 1
UNET Pardiso=0
UNET DZMax Abort= 0
UNET Use Existing IB Tables= 0
UNET Froude Reduction=False
UNET Froude Limit= 0
UNET Froude Power= 0
UNET D1 Cores= 0
UNET WindReference=Eulerian
UNET WindDragFormulation=Hsu (1988)
UNET D2 Coriolis=0
UNET D2 Cores= 0
UNET D2 Theta= 1
UNET D2 Theta Warmup= 1
UNET D2 Z Tol= 0.01
UNET D2 Volume Tol= 0.01
UNET D2 Max Iterations= 20
UNET D2 Equation= 0
UNET D2 RampUpFraction=0.1
UNET D2 TimeSlices= 1
UNET D2 Turbulence Formulation=Non-Conservative (original)
UNET D2 Eddy Viscosity=0.3
UNET D2 Transverse Eddy Viscosity=0.1
UNET D2 Smagorinsky Mixing=0
UNET D2 BCVolumeCheck=0
UNET D2 Cores=0
UNET D2 SolverType=PARDISO (Direct)
UNET D2 Minimum Iterations= 2147483647
UNET D2 Maximum Iterations= 2147483647
UNET D2 Restart Number= 10
UNET D2 Relaxation Coeff=1.3
UNET D2 SOR Precondition Iterations= 10
UNET D2 ILUT Maximum Fill= 8
UNET D2 ILUT Tolerance=1E-08
UNET D1D2 MaxIter= 0
UNET D1D2 ZTol=0.01
UNET D1D2 QTol=0.1
UNET D1D2 MinQTol=1
Write IC File= 0
Write IC File at Fixed DateTime=0
Write IC File at Sim End=0
Echo Input=False
Echo Parameters=False
Echo Output=False
Write Detailed= 0
HDF Write Warmup=0
HDF Write Time Slices=0
HDF Flush=0
HDF Compression= 1
HDF Chunk Size= 1
HDF Spatial Parts= 1
HDF Use Max Rows=0
HDF Fixed Rows= 1
Calibration Method= 0
Calibration Iterations= 20
Calibration Max Change=0.05
Calibration Tolerance=0.2
Calibration Maximum=1.5
Calibration Minimum=0.5
Calibration Optimization Method= 1
WQ AD Non Conservative
WQ ULTIMATE=-1
WQ Max Comp Step=1HOUR
WQ Output Interval=15MIN
WQ Output Selected Increments= 0
WQ Output face flow=0
WQ Output face velocity=0
WQ Output face area=0
WQ Output face dispersion=0
WQ Output cell volume=0
WQ Output cell surface area=0
WQ Output cell continuity=0
WQ Output cumulative cell continuity=0
WQ Output face conc=0
WQ Output face dconc_dx=0
WQ Output face courant=0
WQ Output face peclet=0
WQ Output face adv mass=0
WQ Output face disp mass=0
WQ Output cell mass=0
WQ Output cell source sink temp=0
WQ Output nsm pathways=0
WQ Output nsm derived pathways=0
WQ Create Restart=0
WQ Fixed Restart=0
WQ System Summary=0
WQ Write To DSS=0
Sorting and Armoring Iterations= 10
XS Update Threshold= 0.02
Bed Roughness Predictor= 0
Hydraulics Update Threshold= 0.02
Energy Slope Method= 1
Volume Change Method= 1
Sediment Retention Method= 0
Sediment TS Multiplier= 1
Warm Up Method= 0
XS Weighting Method= 0
Number of US Weighted Cross Sections= 1
Number of DS Weighted Cross Sections= 1
Upstream XS Weight=0
Main XS Weight=1
Downstream XS Weight=0
Number of DS XS's Weighted with US Boundary= 1
Upstream Boundary Weight= 1
Weight of XSs Associated with US Boundary= 0
Number of US XS's Weighted with DS Boundary= 1
Downstream Boundary Weight= 0.5
Weight of XSs Associated with DS Boundary= 0.5
Percentile Method= 0
Sediment Output Level= 3
Mass or Volume Output= 0
Output Increment Type= 1
Profile and TS Output Increment= 1
Transport Output Increment 1
XS Output Flag= 0
XS Output Increment= 10
Read HDF5 Sediment Hotstart= 0
Sediment Hotstart Type= 0
Write Gradation File= 0
Read Gradation Hotstart= 0
Write HDF5 File= 1
Write Binary Output= 1
Write DSS Sediment File= 0
DSS Sediment Output Type= 1
SV Curve= 0
Specific Gage Flag= 0
Subcell Erosion Methods= 0
Subcell Deposition Methods= 0
Advection Scheme= 1
Matrix Solver= 0
Implicit Weighting Factor= 1
Maximum Outer Loop Convergence Iterations= 5
Convergence Maximum Absolute= 0.001
Convergence RMSE= 0.0001
Grain Fractions Max Abs Error= 0.001
Max Subgrid Regions= 1
Max Subgrid Length Scale= 3.402823E+38
Initial Layer Thickness= 3.402823E+38
Min Layer Thickness= 3.402823E+38
Max Layer Thickness= 3.402823E+38
Number of Layers= 5

--- GRNBRRRVT1.f01 (steady flow) ---

Flow Title=Flow
Program Version=6.00
Number of Profiles= 6
Profile Names=01pct,10pct,04pct,02pct,0_2pct,01plus
River Rch & RM=GRNBRRRVT1,Main            ,2172
     518     273     364     438     725     767
Boundary for River Rch & Prof#=GRNBRRRVT1,Main            , 1
Up Type= 0
Dn Type= 3
Dn Slope=0.01792
Boundary for River Rch & Prof#=GRNBRRRVT1,Main            , 2
Up Type= 0
Dn Type= 3
Dn Slope=0.01792
Boundary for River Rch & Prof#=GRNBRRRVT1,Main            , 3
Up Type= 0
Dn Type= 3
Dn Slope=0.01792
Boundary for River Rch & Prof#=GRNBRRRVT1,Main            , 4
Up Type= 0
Dn Type= 3
Dn Slope=0.01792
Boundary for River Rch & Prof#=GRNBRRRVT1,Main            , 5
Up Type= 0
Dn Type= 3
Dn Slope=0.01792
Boundary for River Rch & Prof#=GRNBRRRVT1,Main            , 6
Up Type= 0
Dn Type= 3
Dn Slope=0.01792
DSS Import GetInterval= 0
DSS Import GetPeak= 0
DSS Import FillOption= 0

--- GRNBRRRVT1.g01 (geometry) ---

Geom Title=Geometry
Program Version=6.10

River Reach=GRNBRRRVT1      ,Main
Reach XY= 30
     2303528.466      584693.5642303804.88483416584656.605678238
     2303962.119      584551.068      2304017.93       584561.96
 2304059.1686584584591.4390247962304167.63645228584567.508673077
2304186.90123498584551.7815543142304215.04384188584499.203861111
2304243.63287464      584466.106     2304285.781      584434.565
     2304369.378      584394.2682304451.74512536584332.773188034
2304490.92277699584274.288532958 2304489.2794173584217.944772276
2304532.41541097584160.5999779222304554.77903909584151.975619145
2304644.69429051 584144.008078092304729.13793078 584064.39976617
2304746.22186325584059.2562099592304781.04286156 584054.72220463
2304828.64102915584067.5654991642304943.35010924584044.105301536
 2305008.1548077584052.295355398 2305057.4314523584086.901192299
     2305107.312      584141.565     2305109.371       584160.36
2305095.66116061584188.2747680112305099.48058772584201.901724639
2305150.51048917584251.274735132     2305226.286      584352.873

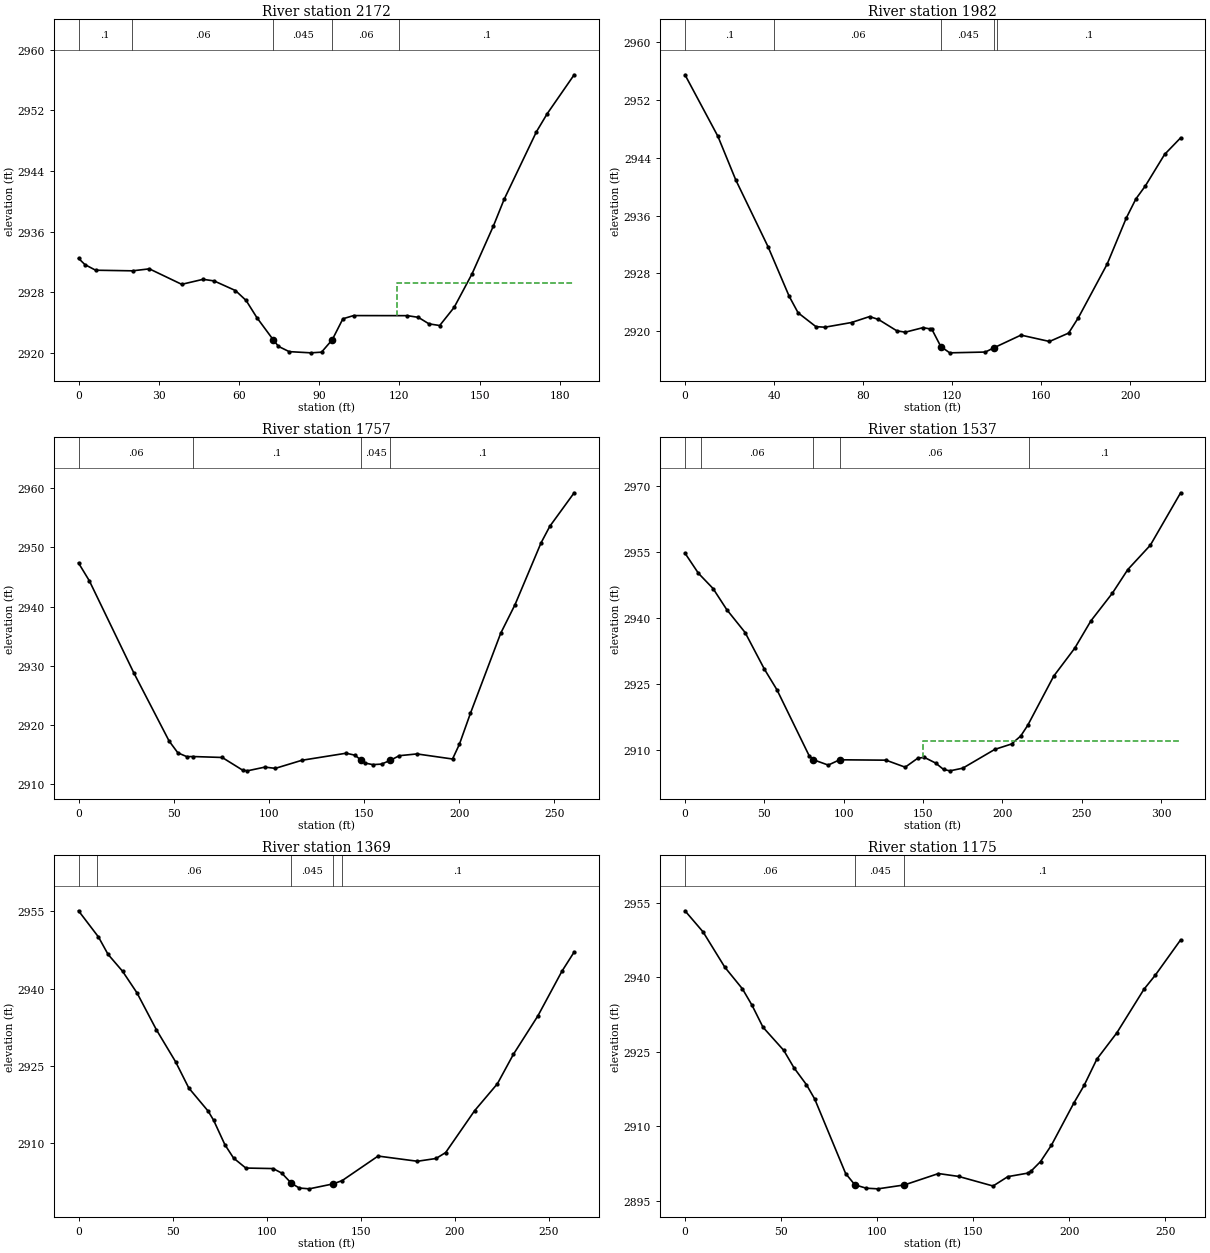
Type RM Length L Ch R = 1 ,2172    ,189.4,189.4,189.4
XS GIS Cut Line= 2
2303551.97847016584775.5702908192303532.85326139584591.125480776
#Sta/Elev= 30
       0 2932.49     2.4 2931.66     6.4 2930.92    20.2 2930.84    26.5  2931.1
    38.6 2929.06    46.6 2929.72    50.7 2929.51    58.7 2928.24    62.7 2926.93
    66.7 2924.68    72.92921.719    74.8 2920.88    78.8 2920.19    86.9 2920.03
    90.9 2920.12    94.9 2921.75    98.9 2924.52   102.9 2924.94     123 2924.93
   127.1 2924.71   131.1 2923.85   135.1 2923.63   140.5 2926.02   147.2 2930.44
   155.2 2936.76   159.2 2940.26   171.3 2949.18   175.3 2951.54   185.4 2956.68
#Mann= 5 ,-1,0
       0      .1       0      20     .06       0    72.9    .045       0
    94.9     .06       0     120      .1       0
#XS Ineff= 2 , 0
                          118.99          2929.3
Permanent Ineff=
       F       F
Bank Sta=72.9,94.9
XS Rating Curve= 0 ,0
Exp/Cntr(USF)=0,0
Exp/Cntr=0.3,0.1

Type RM Length L Ch R = 1 ,1982    ,234.1,225.7,217
XS GIS Cut Line= 3
 2303734.8024998584795.9921239172303730.26431467584644.287078047
2303704.00767211 584578.48339362
#Sta/Elev= 30
       0 2955.45    14.8 2946.94    22.8 2940.93    37.3  2931.7    46.8 2924.85
    50.8 2922.57    58.8 2920.66    62.8 2920.58    74.8 2921.23    82.9 2922.05
    86.9 2921.65    95.1 2920.09    98.9 2919.89   106.9 2920.52   110.2 2920.34
   110.9 2920.28   114.9 2917.91   118.9 2917.04   134.9 2917.15   138.9 2917.76
   150.9 2919.49   163.7 2918.61   172.3 2919.77   176.7 2921.91   189.6  2929.3
   198.2 2935.67   202.5  2938.3   206.8 2940.12   215.4 2944.45   222.6 2946.74
#Mann= 5 ,-1,0
       0      .1       0      40     .06       0   114.9    .045       0
   138.9     .06       0     140      .1       0
Bank Sta=114.9,138.9
XS Rating Curve= 0 ,0
Exp/Cntr(USF)=0,0
Exp/Cntr=0.3,0.1

Type RM Length L Ch R = 1 ,1757    ,215.3,219.9,224.5
XS GIS Cut Line= 2
2304005.46101342584702.0808846892303872.49041905584478.226718944
#Sta/Elev= 30
       0 2947.38     5.7 2944.36      29 2928.83    47.6 2917.27    52.2 2915.27
    56.9 2914.63      60 2914.65    75.5 2914.49    86.2 2912.35    88.7 2912.23
    97.9 2912.86   103.4 2912.65   117.4 2914.02   140.6 2915.21   145.3 2914.87
   148.52914.008   150.5 2913.55   154.6 2913.28   159.2 2913.37   163.9 2914.02
   168.5 2914.79   177.8 2915.09   196.5 2914.23   200.1 2916.72   205.9 2921.96
   221.8 2935.49   229.3 2940.31     243 2950.78   247.6 2953.58   260.4 2959.25
#Mann= 4 ,-1,0
       0     .06       0      60      .1       0   148.5    .045       0
   163.9      .1       0
Bank Sta=148.5,163.9
XS Rating Curve= 0 ,0
Exp/Cntr(USF)=0,0
Exp/Cntr=0.3,0.1

Type RM Length L Ch R = 1 ,1537    ,172.7,167.8,159.2
XS GIS Cut Line= 3
2304140.26147835584666.7033871052304114.03333359584471.517193541
2304054.25756181584372.704183048
#Sta/Elev= 30
       0 2954.78     8.5 2950.18    17.7 2946.72    26.3 2941.93    37.9  2936.7
      50 2928.39      58 2923.63    78.2 2908.68    80.9 2907.72    90.3  2906.5
    97.5 2907.71   126.7 2907.62   138.8 2906.02   146.8 2908.09   150.9 2908.25
     158 2906.96     163  2905.5     167 2905.19   175.1  2905.8   195.3 2910.08
   205.8  2911.3   211.6 2913.12     216 2915.54   232.4 2926.76   245.7 2933.15
   255.8 2939.33   269.4 2945.67   279.1 2951.04   293.3 2956.59   312.4 2968.53
#Mann= 5 ,-1,0
       0      .1       0      10     .06       0    80.9    .045       0
    97.5     .06       0  216.94      .1       0
#XS Ineff= 2 , 0
                          149.82         2912.06
Permanent Ineff=
       F       F
Bank Sta=80.9,97.5
XS Rating Curve= 0 ,0
Exp/Cntr(USF)=0,0
Exp/Cntr=0.3,0.1

Type RM Length L Ch R = 1 ,1369    ,195.1,193.8,192.6
XS GIS Cut Line= 2
 2304320.8087074584565.4505491942304156.12035658584359.895089096
#Sta/Elev= 30
       0 2955.11    10.6 2950.02    15.7 2946.64    23.4 2943.36    31.1 2939.14
    41.4 2931.98    51.6 2925.76    58.6 2920.67    68.9 2916.17    71.8  2914.4
    77.8 2909.64    82.4 2907.05    88.9 2905.11   103.4 2905.01     108 2904.13
   113.1 2902.16   117.3 2901.23   122.6 2901.07   135.4 2902.04   140.1 2902.67
   159.2 2907.44   180.1 2906.43     190 2906.97   195.1 2908.12   210.5 2916.26
   222.6 2921.49   231.1 2927.21   244.1 2934.67   256.9 2943.36   263.4  2947.1
#Mann= 5 ,-1,0
       0      .1       0      10     .06       0   113.1    .045       0
   135.4     .06       0     140      .1       0
Bank Sta=113.1,135.4
XS Rating Curve= 0 ,0
Exp/Cntr(USF)=0,0
Exp/Cntr=0.3,0.1

Type RM Length L Ch R = 1 ,1175    ,248.8,248.4,246.9
XS GIS Cut Line= 2
2304475.12779168584443.459178216 2304303.1199586584251.322768925
#Sta/Elev= 30
       0 2953.41     9.4 2949.16    20.7 2942.06    29.9 2937.68    34.9 2934.37
    40.6 2929.95    51.4 2925.29    56.7 2921.79    63.2 2918.38    67.5  2915.5
    83.6 2900.48    88.4 2898.21    94.3 2897.53   100.4  2897.4   114.2 2898.19
   131.9 2900.48   142.4  2899.9   160.3 2897.97     168 2899.86   178.3 2900.56
   180.2 2901.02     185 2902.89   190.7 2906.21   202.3 2914.66   207.7 2918.25
   214.3 2923.52   224.7 2928.82   238.8 2937.59   244.7 2940.43   257.9 2947.55
#Mann= 3 ,0,0
       0     .06       0    88.4    .045       0   114.2      .1       0
Bank Sta=88.4,114.2
XS Rating Curve= 0 ,0
Exp/Cntr(USF)=0,0
Exp/Cntr=0.3,0.1

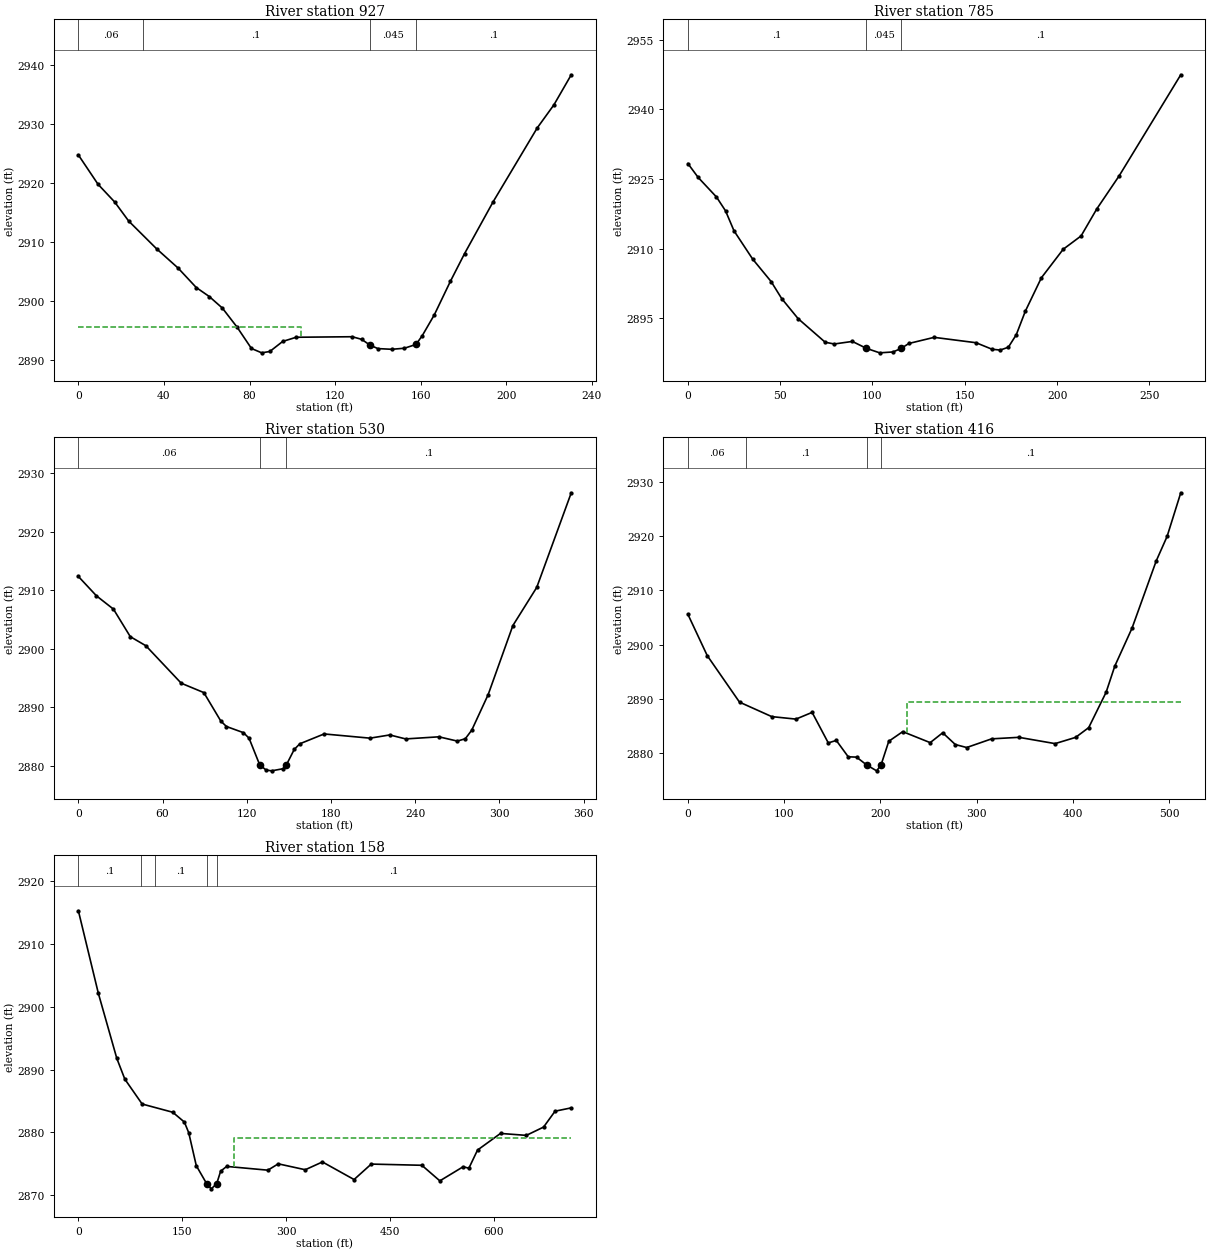
Type RM Length L Ch R = 1 ,927     ,140,141.9,144.6
XS GIS Cut Line= 3
2304611.14817032 584283.040525382304542.22304572584186.057385452
2304467.80830942584103.103253187
#Sta/Elev= 30
       0 2924.79     9.2 2919.82      17 2916.81    23.5  2913.6    36.6 2908.88
    46.6 2905.63    55.1 2902.33    61.2  2900.8    67.3 2898.85    74.2 2895.61
    80.9    2892    85.7 2891.26    89.5 2891.49    95.5 2893.19   101.8  2893.9
     128 2893.99   132.4 2893.55   136.3 2892.57     140 2891.98   146.5 2891.86
   152.4 2892.04   157.8 2892.68   160.7 2894.14   166.4 2897.71   173.9 2903.38
   180.5 2908.06   193.9 2916.87   214.5 2929.38   222.3 2933.29   230.4 2938.38
#Mann= 4 ,-1,0
       0     .06       0      30      .1       0   136.3    .045       0
   157.8      .1       0
#XS Ineff= 2 , 0
          104.29 2895.59
Permanent Ineff=
       F       F
Bank Sta=136.3,157.8
XS Rating Curve= 0 ,0
Exp/Cntr(USF)=0,0
Exp/Cntr=0.3,0.1

Type RM Length L Ch R = 1 ,785     ,248.3,255.4,262.4
XS GIS Cut Line= 3
2304718.50057678584217.7751419062304636.76635823584103.103253187
2304585.52998242583987.821407613
#Sta/Elev= 30
       0 2928.34     5.6 2925.33    15.5 2921.12    20.4 2918.14      25 2913.82
    35.1 2907.73    45.1 2902.89    50.8 2899.23    59.7  2894.9    74.4  2889.8
    79.3 2889.43    89.1 2889.98    96.7 2888.49   103.9 2887.52   111.1 2887.71
   115.52888.465   119.7 2889.54   133.4 2890.86   156.1  2889.7   164.8 2888.29
   169.2 2888.12   173.6 2888.73   177.9 2891.43   182.8  2896.5   191.5 2903.71
   203.3 2909.85     213 2912.73   221.5 2918.55   233.6 2925.67     267 2947.48
#Mann= 3 ,-1,0
       0      .1       0    96.7    .045       0   115.5      .1       0
Bank Sta=96.7,115.5
XS Rating Curve= 0 ,0
Exp/Cntr(USF)=0,0
Exp/Cntr=0.3,0.1

Type RM Length L Ch R = 1 ,530     ,107.6,113.9,118.1
XS GIS Cut Line= 3
2304896.60797841584193.9868245662304877.08935906584023.808862051
2304745.94863525583900.597577363
#Sta/Elev= 30
       0 2912.34    12.9 2909.03      25 2906.76      37 2902.06    48.1 2900.51
    73.3 2894.11    89.4 2892.51   101.5 2887.65   105.5 2886.72   117.6 2885.67
   121.6 2884.73  129.16  2880.2   133.7 2879.29   137.7 2879.15   145.8 2879.51
  148.22 2880.17   153.8  2882.8   157.8 2883.77   175.1 2885.45   207.8 2884.73
   221.9 2885.28   233.2  2884.6   256.9 2884.96     270 2884.23   275.7 2884.63
   280.3  2886.1     292 2892.17   309.6 2903.96   326.6 2910.47   351.2 2926.63
#Mann= 3 ,0,0
       0     .06       0  129.16    .045       0  148.22      .1       0
Bank Sta=129.16,148.22
XS Rating Curve= 0 ,0
Exp/Cntr(USF)=0,0
Exp/Cntr=0.3,0.1

Type RM Length L Ch R = 1 ,416     ,247.6,257.7,261.4
XS GIS Cut Line= 4
2304935.03526027584232.4141064242304999.69068689584023.808862051
2304981.64359833 583980.716004272304763.63738405 583865.22007978
#Sta/Elev= 30
       0 2905.61    20.1 2897.99    53.6 2889.41    87.1 2886.74   112.2 2886.28
     129 2887.52   145.8 2881.89   154.1 2882.35   166.5 2879.33   175.1 2879.27
   185.7 2877.82     196 2876.74  200.55 2877.82   208.6 2882.19   223.1 2883.97
   251.6 2881.94   264.6 2883.76   277.7 2881.59   289.5 2881.04   315.4 2882.64
   343.7 2882.92   381.3 2881.76   402.6 2882.91   416.2 2884.71   434.3 2891.24
   443.3 2896.06   461.2 2903.06   486.3 2915.45   497.6 2919.97   511.8 2928.02
#Mann= 4 ,-1,0
       0     .06       0      60      .1       0   185.7    .045       0
  200.55      .1       0
#XS Ineff= 2 , 0
                          227.83         2889.45
Permanent Ineff=
       F       F
Bank Sta=185.7,200.55
XS Rating Curve= 0 ,0
Exp/Cntr(USF)=0,0
Exp/Cntr=0.3,0.1

Type RM Length L Ch R = 1 ,158     ,,,
XS GIS Cut Line= 4
 2304989.8243513584363.6941847992305152.93023961584206.744045022
2305187.63983708584082.0619648232305093.63911542583738.547688461
#Sta/Elev= 30
       0 2915.27    28.9 2902.11    55.5 2891.78    67.1 2888.47    92.1 2884.51
   136.3  2883.2   153.1 2881.64   159.4 2879.94   170.3  2874.7  185.23 2871.84
     192 2871.01   199.8 2871.84   205.5 2873.82   214.2 2874.58   273.7 2873.98
   288.7 2874.99   327.7 2874.05   352.5 2875.29   398.2 2872.49     423 2874.95
   496.1 2874.76   522.1 2872.28   555.8 2874.53     564 2874.29   576.5 2877.18
   609.7 2879.83     647 2879.52   671.9 2880.84   688.5 2883.37   711.9  2883.9
#Mann= 5 ,-1,0
       0      .1       0      90     .06       0     110      .1       0
  185.23    .045       0   199.8      .1       0
#XS Ineff= 2 , 0
                          224.58         2879.15
Permanent Ineff=
       F       F
Bank Sta=185.23,199.8
XS Rating Curve= 0 ,0
Exp/Cntr(USF)=0,0
Exp/Cntr=0.3,0.1
LCMann Table=0

Chan Stop Cuts=-1
Use User Specified Reach Order=0
Composite Channel Slope=5